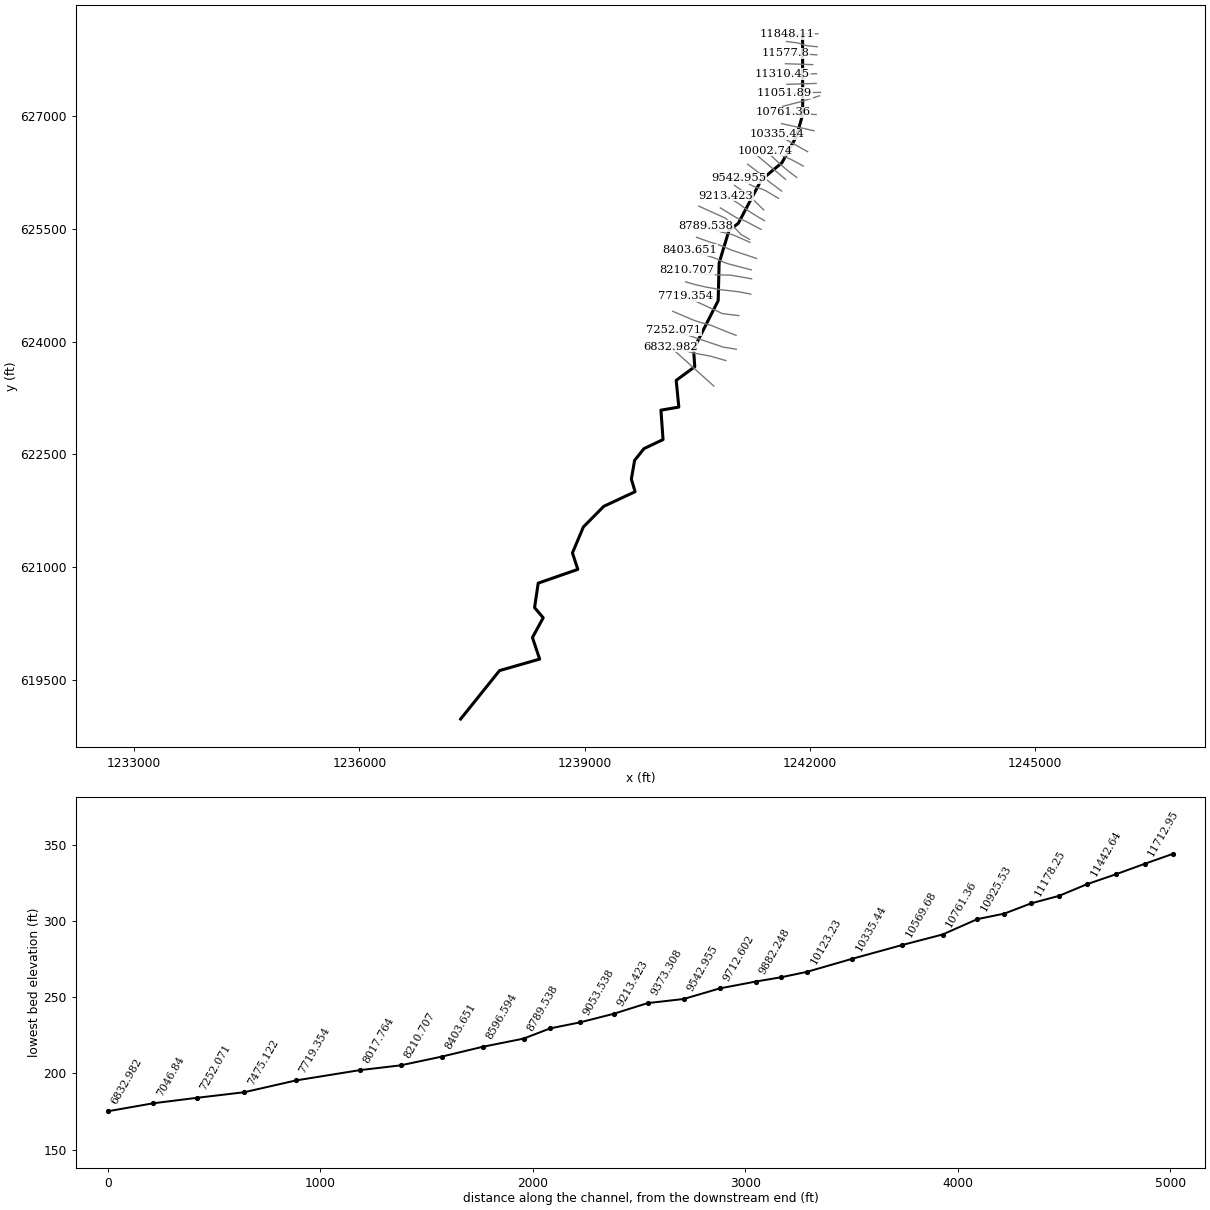
--- 335_ras.prj (project) ---

Proj Title=335
Current Plan=p01
Default Exp/Contr=0.3,0.1
English Units
Geom File=g01
Flow File=f01
Plan File=p01
Y Axis Title=Elevation
X Axis Title(PF)=Main Channel Distance
X Axis Title(XS)=Station
BEGIN DESCRIPTION:
RFD model 335 exported to HEC-RAS
END DESCRIPTION:

--- 335_ras.p01 (plan) ---

Plan Title=Plan 01
Program Version=4.10
Short Identifier=Plan 01
Geom File=g01
Flow File=f01
Subcritical Flow
Calc Critical at every XS
Secant Critical Depth

--- 335_ras.f01 (steady flow) ---

Flow Title=Flow 01
Program Version=5.01
Number of Profiles= 5
Profile Names=10yr,25yr,50yr,100yr,500yr
River Rch & RM=335,40,11848.11
  370.78  440.08  524.05   556.1  647.83
River Rch & RM=335,40,11712.95
  379.93  452.55  539.33  574.39  672.24
River Rch & RM=335,40, 11577.8
  385.26  459.83  548.27  585.11   686.6
River Rch & RM=335,40,11442.64
  391.35  468.16  558.49   597.4  703.11
River Rch & RM=335,40,11310.45
  408.77  492.13  587.93  632.97  751.14
River Rch & RM=335,40,11178.25
  415.12   500.9  598.71  646.04  768.91
River Rch & RM=335,40,11051.89
  429.63  521.02  623.47  676.18  810.04
River Rch & RM=335,40,10925.53
  434.79  528.19  632.31  686.98  824.84
River Rch & RM=335,40,10761.36
  442.71  539.24  645.92  703.65  847.75
River Rch & RM=335,40,10569.68
  460.62  564.32  676.85  741.68  900.33
River Rch & RM=335,40,10335.44
  474.35  583.64   700.7  771.16  941.34
River Rch & RM=335,40,10123.23
  486.26  600.47   721.5  796.97  977.43
River Rch & RM=335,40,9882.248
  503.63  625.11  751.99  834.96 1030.87
River Rch & RM=335,40,9712.602
  509.98  634.16  763.18  848.97 1050.66
River Rch & RM=335,40,9542.955
  524.53  654.94  788.93  881.27 1096.47
River Rch & RM=335,40,9373.308
  527.26  658.84  793.77  887.36 1105.14
River Rch & RM=335,40,9213.423
  534.79  669.63  807.15  904.21 1129.15
River Rch & RM=335,40,9053.538
  537.44  673.44  811.87  910.16 1137.65
River Rch & RM=335,40,8915.834
  542.16  680.22  820.28  920.78 1152.84
River Rch & RM=335,40,8789.538
   546.3  686.18  827.68  930.13 1166.22
River Rch & RM=335,40,8596.594
  719.26  940.49 1144.84 1339.98  1770.1
River Rch & RM=335,40,8403.651
  730.94  958.01 1166.78 1368.92 1813.86
River Rch & RM=335,40,8210.707
   739.1  970.28 1182.17 1389.25 1844.69
River Rch & RM=335,40,8017.764
  746.49  981.41 1196.12 1407.72 1872.74
River Rch & RM=335,40,7719.354
  751.25  988.59 1205.13 1419.65 1890.89
River Rch & RM=335,40,7475.122
   759.4 1000.88 1220.55 1440.12 1922.08
River Rch & RM=335,40,7252.071
  764.65 1008.82 1230.51 1453.35 1942.29
River Rch & RM=335,40, 7046.84
   766.8 1012.07 1234.59 1458.77 1950.57
River Rch & RM=335,40,6832.982
     778 1029.03 1255.88 1487.12 1993.95
River Rch & RM=335,40,6654.258
  780.69 1033.11    1261 1493.94  2004.4
River Rch & RM=335,40,6487.424
  784.84 1039.41 1268.91  1504.5  2020.6
River Rch & RM=335,40,6165.262
   791.3 1049.22 1281.24 1520.95 2045.87
River Rch & RM=335,40,5924.215
  796.81  1057.6 1291.77 1535.03 2067.53
Boundary for River Rch & Prof#=335,40,1
Up Type= 0
Dn Type= 2
Boundary for River Rch & Prof#=335,40,2
Up Type= 0
Dn Type= 2
Boundary for River Rch & Prof#=335,40,2
Up Type= 0
Dn Type= 2
Boundary for River Rch & Prof#=335,40,2
Up Type= 0
Dn Type= 2
Boundary for River Rch & Prof#=335,40,2
Up Type= 0
Dn Type= 2

--- 335_ras.g01 (geometry) ---

Geom Title=335
Program Version=4.10

River Reach=335,40
Reach XY= 30
1241900.82639003628094.9595390721241902.49302508627026.626522816
1241819.15970781626734.126612077 1241625.8264213 626383.29338852
1241351.65982889626155.7934640251241044.99323586625577.460311299
1240920.82660304625481.6270100681240789.99329573625049.960475311
1240777.49328481624548.293957949 1240449.1600295 623900.79415974
1240465.82668447 623668.29422829 1240218.3267522623486.627622759
1240253.32673151623130.7943940331240014.99346732623089.961079755
1240043.32678088622698.294528548 1239789.1601857 622577.46123848
1239664.54039183622420.9330869731239621.20706403622171.766495555
 1239671.2070444622004.2665438071239253.70716191621809.266613846
1238982.87390052 621535.100036481238837.04060015621189.266810046
1238908.70723928620970.100206372 1238381.2073896620786.766942798
1238332.87406105620460.9337076141238447.88257138620325.895769134
1238304.54927268620062.5625181531238400.38256939619775.895933823
1237866.21605588619622.5626615431237348.72908476618977.919293303

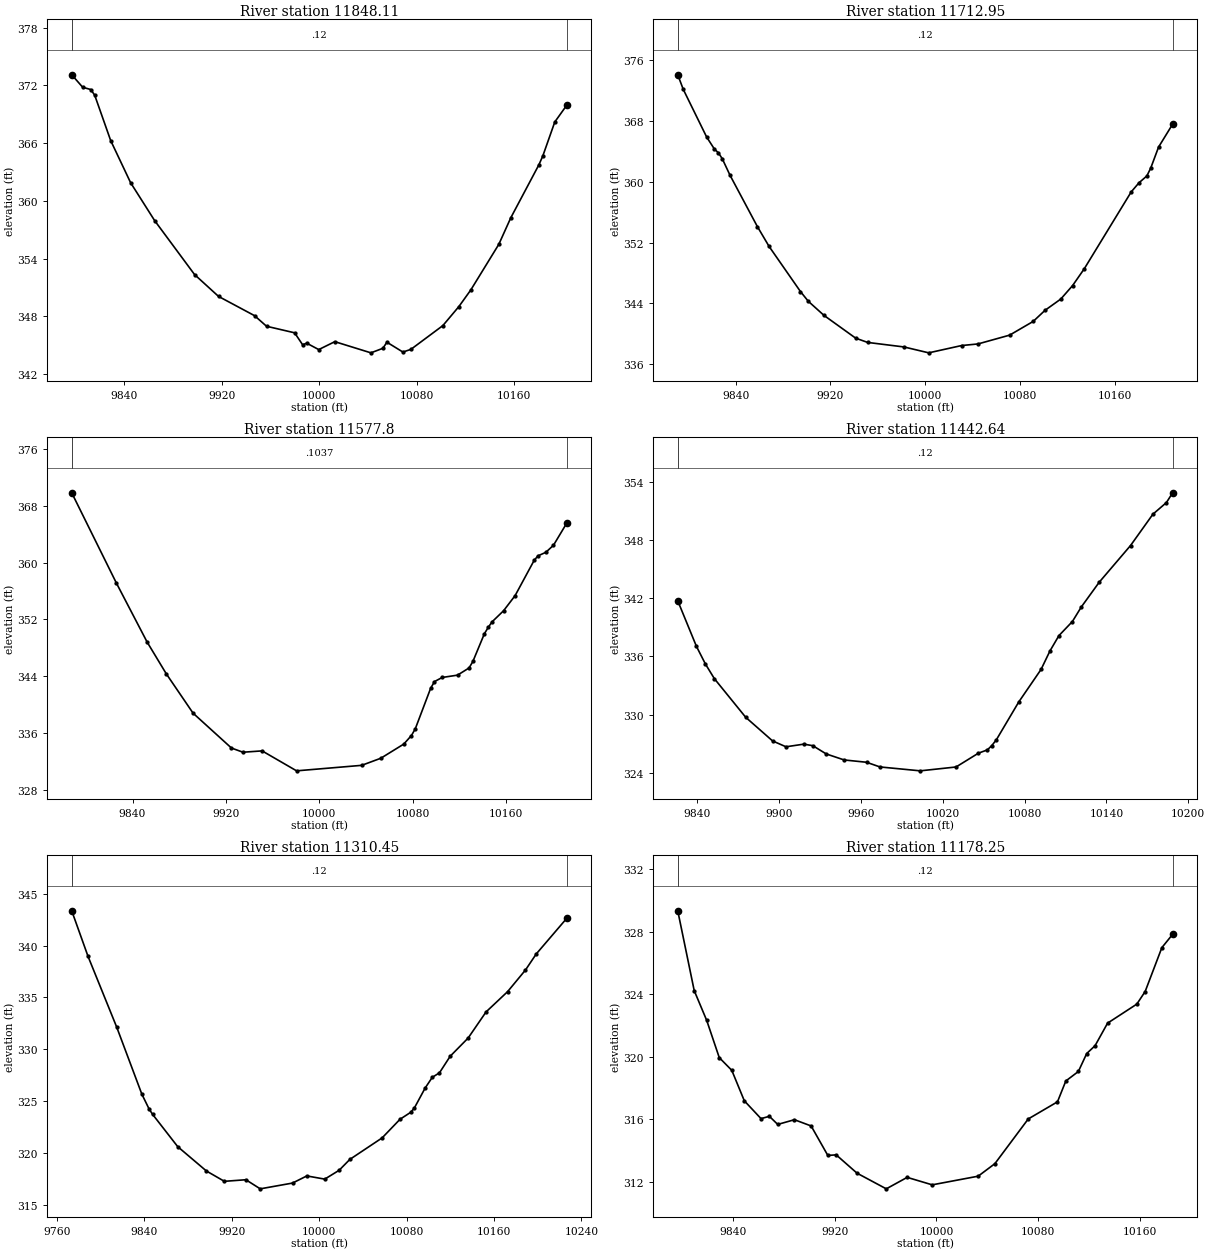
Type RM Length L Ch R = 1 ,11848.11,135.155600,135.155600,135.155600
XS GIS Cut Line= 6
1242103.91531463 628100.618772971241973.45845113628100.176157403
1241869.69304808628090.6053743791241828.39717248628088.699952229
1241773.01190658628089.3543605411241698.02083256628092.972690103
#Sta/Elev= 30
9796.756373.11269805.781371.81149812.343371.58099815.624370.99189828.747366.2701
9845.151361.87929864.837357.94799897.645352.3318 9917.33350.0597  9946.9348.0568
9956.763346.95459979.824346.27249986.426345.02479989.728345.19699999.633344.5275
10012.84345.351910042.48344.189410052.33 344.66210055.62345.296110068.75344.2711
10075.32344.550910101.57347.023410114.69348.996310124.54350.734710147.52 355.475
10157.38358.241410180.37363.730910183.66364.666510193.51368.206610203.25369.9324
#Mann= 3 , 0 , 0
9796.756    0.12       09796.756    0.12       010203.25    0.12       0
#XS Ineff= 2 , 0
       0                               0
Bank Sta=9796.756,10203.25
Exp/Cntr=0.3,0.1

Type RM Length L Ch R = 1 ,11712.95,135.155600,135.155600,135.155600
XS GIS Cut Line= 6
1242096.22196577 627928.005664491241968.05555778627940.993963807
1241923.62159514627950.5881513081241863.94178711 627971.24028094
1241827.50373467627980.4003537311241686.06721073627997.870318978
#Sta/Elev= 30
9791.207374.03639795.834372.12549815.582365.86149822.165364.26859825.456363.7927
9828.747363.0157 9835.33360.83089858.369354.10229868.284351.48689894.736345.5663
9901.349344.28849914.576342.43539941.344339.44189951.414338.88289982.136338.2863
10002.96337.514810030.73338.4742 10044.5338.682510071.23339.840510091.14341.6459
 10101.1343.101210114.37344.578510124.33346.346310134.24348.566510173.82 358.657
10180.41359.856410187.01360.7494 10190.3361.7887 10196.9364.5454 10208.8367.5618
#Mann= 3 , 0 , 0
9791.207    0.12       09791.207    0.12       0 10208.8    0.12       0
#XS Ineff= 2 , 0
       0                               0
Bank Sta=9791.207,10208.8
Exp/Cntr=0.3,0.1

Type RM Length L Ch R = 1 , 11577.8,135.155600,135.155600,135.155600
XS GIS Cut Line= 6
1242090.47268211627820.3179541081241938.97044381 627829.14100269
1241879.64528486627829.415158521 1241877.6456277627829.378127891
1241805.87549079627830.3692197061241666.95581219627840.613325959
#Sta/Elev= 30
9787.915 369.8489826.213357.12319852.504348.82599868.936344.34969891.941338.7961
9924.805333.88939934.664333.30059951.077 333.4889980.605330.677710036.38331.4514
10052.79332.450810072.48334.447610079.05335.654410082.34336.5959 10095.5342.3044
10098.79343.251510105.37343.829710118.53344.1588 10128.4 345.16810131.69346.0817
10141.56349.991310144.85350.886610148.14 351.66510158.01353.232110167.88355.3598
10184.33360.363710187.62360.9735 10194.2361.459610200.77362.453710212.07365.5539
#Mann= 3 , 0 , 0
9787.915  0.1037       09787.915  0.1037       010212.07  0.1037       0
#XS Ineff= 2 , 0
       0                               0
Bank Sta=9787.915,10212.07
Exp/Cntr=0.3,0.1

Type RM Length L Ch R = 1 ,11442.64,132.196700,132.196700,132.196700
XS GIS Cut Line= 2
1242036.43896797627690.0199936181241673.59174573627702.172771409
#Sta/Elev= 30
9825.528341.72879839.263337.02729845.828335.21519852.394333.70549875.372 329.726
9895.069327.29259904.917326.68679918.047326.95919924.613326.79969934.461325.9484
9947.591325.33099964.005325.09239973.853324.6099 10003.4324.208610029.66324.6057
10046.07326.028910052.64326.367210055.92326.8179 10059.2327.400110075.62331.2948
10092.03334.659410098.59336.572510105.16338.146910115.01339.594710121.57341.0992
 10134.7343.646310157.68347.4279 10174.1350.657210183.94351.846810188.58352.8604
#Mann= 3 , 0 , 0
9825.528    0.12       09825.528    0.12       010188.58    0.12       0
#XS Ineff= 2 , 0
       0                               0
Bank Sta=9825.528,10188.58
Exp/Cntr=0.3,0.1

Type RM Length L Ch R = 1 ,11310.45,132.196800,132.196800,132.196800
XS GIS Cut Line= 5
1242086.87111583627569.8343824631241906.06112107627563.442971946
1241861.48509948627563.7186834051241859.48549936627563.758675466
1241633.99082498 627564.56482162
#Sta/Elev= 30
  9773.5343.37269788.456338.96199814.719332.12629837.699325.66159844.265324.2446
9847.548323.71259870.528 320.5969896.791 318.2479913.206317.25059932.903317.4034
9946.035316.52499975.568317.08219988.691317.7713 10005.1317.462710018.22318.3143
10028.06319.367510057.59321.443110073.99323.243610083.84323.919710087.12324.3333
10096.96326.256210103.52327.294310110.08327.726110119.93329.332410136.33331.0862
10152.73333.607210172.42335.562710188.82337.655610198.67 339.205 10226.5342.6355
#Mann= 3 , 0 , 0
  9773.5    0.12       0  9773.5    0.12       0 10226.5    0.12       0
#XS Ineff= 2 , 0
       0                               0
Bank Sta=9773.5,10226.5
Exp/Cntr=0.3,0.1

Type RM Length L Ch R = 1 ,11178.25,126.357500,126.357500,126.357500
XS GIS Cut Line= 2
1242081.57785684627440.0199936331241692.68896794627427.867215842
#Sta/Elev= 30
 9796.65 329.3269809.591324.22449819.438322.31679829.286319.94349839.133319.1319
 9848.98317.1852 9862.11316.04639868.675316.1942 9875.24315.67599888.369 315.977
9901.499315.57819914.629313.69419921.194313.73169937.606312.56029960.583311.5605
9976.995312.2936 9996.69311.8161 10032.8312.368810045.93313.166910072.19316.0262
10095.16317.120210101.73318.452510111.58319.058110118.14320.2054 10124.7320.7046
10134.55322.146810157.53323.362810164.09324.167710177.22326.971910185.73327.8261
#Mann= 3 , 0 , 0
 9796.65    0.12       0 9796.65    0.12       010185.73    0.12       0
#XS Ineff= 2 , 0
       0                               0
Bank Sta=9796.65,10185.73
Exp/Cntr=0.3,0.1

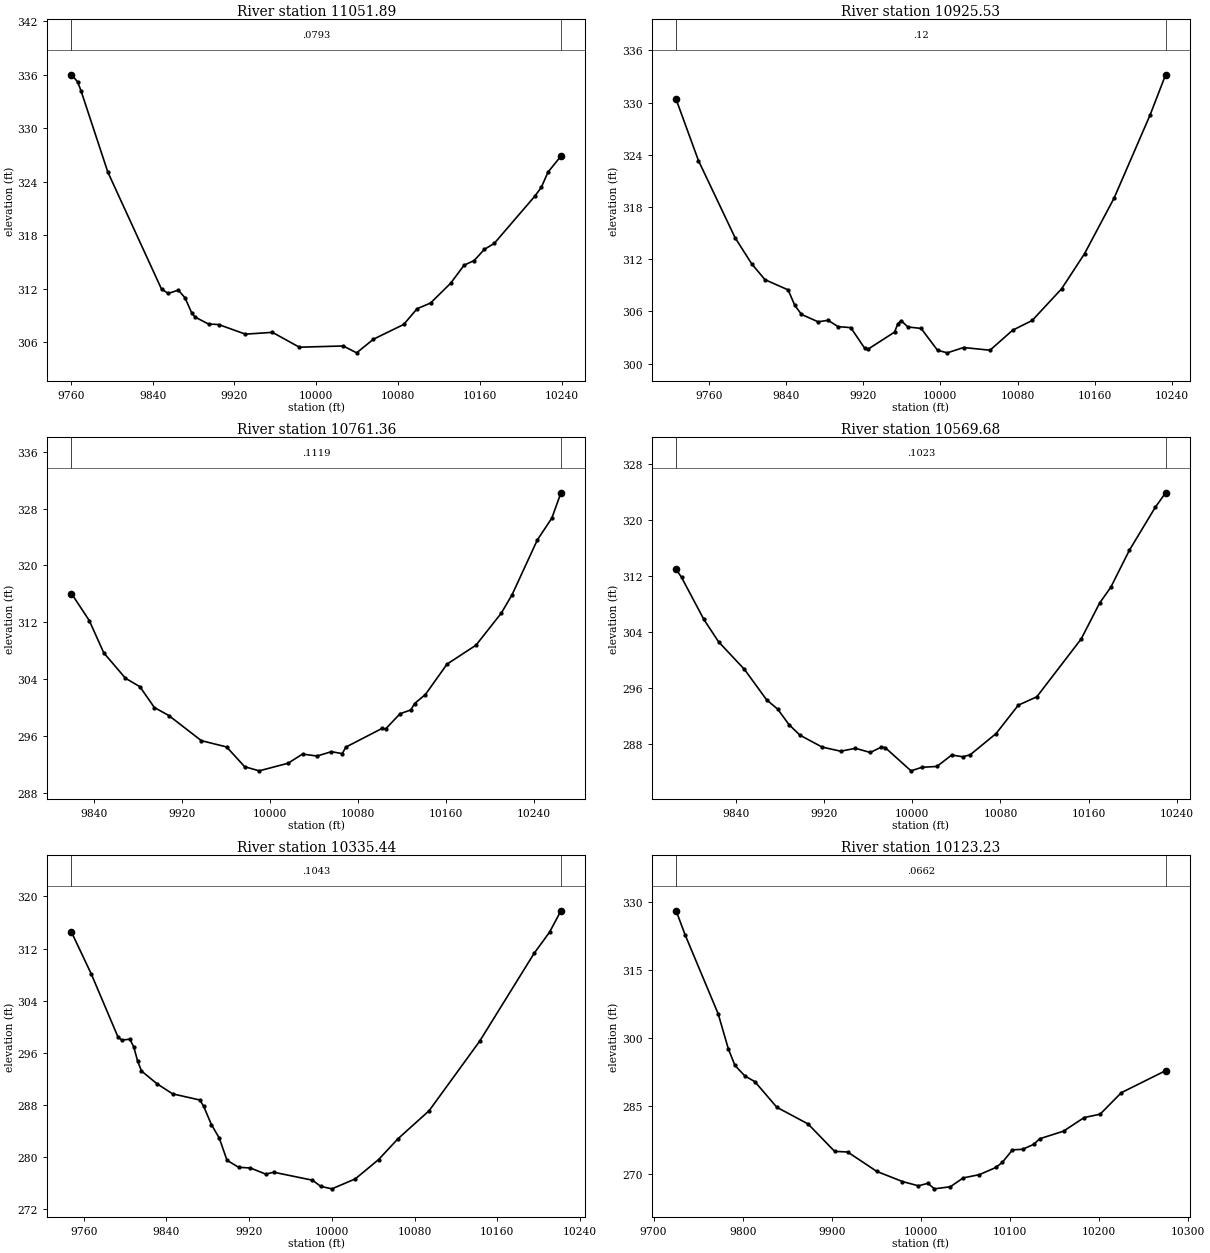
Type RM Length L Ch R = 1 ,11051.89,126.357600,126.357600,126.357600
XS GIS Cut Line= 6
1242140.28615674627321.0598230161241972.58945727627317.003590411
1241902.33123525627310.2523076941241900.34747192627309.997979119
1241855.97708946627306.0331086321241662.30669742627312.451942909
#Sta/Elev= 30
9760.672335.9995  9766.7335.20779769.982334.22069796.236325.08929848.745311.9692
9855.308311.48229865.154311.85659871.717310.99529878.281 309.2959881.563308.8312
 9894.69308.05349904.535307.9999  9930.8306.91939957.167307.12259983.535305.4558
10026.37305.594510039.55304.824210055.98306.354810085.53308.004710098.66309.7729
10111.79310.404410131.48312.629810144.61314.651910154.46315.172610164.31316.4149
10174.16317.100910213.55322.360310220.11323.374410226.68325.089510239.32326.8787
#Mann= 3 , 0 , 0
9760.672  0.0793       09760.672  0.0793       010239.32  0.0793       0
#XS Ineff= 2 , 0
       0                               0
Bank Sta=9760.672,10239.32
Exp/Cntr=0.3,0.1

Type RM Length L Ch R = 1 ,10925.53,164.176300,164.176300,164.176300
XS GIS Cut Line= 4
1242126.80438596627275.3648787891241879.73407349627196.751597539
1241819.26231864627182.0655999331241639.57481867627135.415960521
#Sta/Elev= 30
9726.306330.37559749.468323.3253 9787.34314.47979804.554311.47639818.326309.6474
 9842.31308.47349849.312306.68289856.198305.65079873.412 304.8019883.741304.9746
 9894.07  304.259907.234304.13229921.613301.77259925.056301.64799952.599 303.617
9956.042 304.5839959.485304.93439966.371304.21089980.143304.03889997.129301.5304
10007.26301.234210024.14301.846210051.51301.536110074.89303.830310095.23 304.957
10125.73308.601810149.46312.635210179.97319.005610217.25328.549710233.46333.2011
#Mann= 3 , 0 , 0
9726.306    0.12       09726.306    0.12       010233.46    0.12       0
#XS Ineff= 2 , 0
       0                               0
Bank Sta=9726.306,10233.46
Exp/Cntr=0.3,0.1

Type RM Length L Ch R = 1 ,10761.36,191.676600,191.676600,191.676600
XS GIS Cut Line= 2
1242081.57785684627025.0894380661241637.13341242627052.867215857
#Sta/Elev= 30
9819.063316.0549 9835.31312.24419848.459 307.7089868.182 304.1419881.331302.9476
 9894.48300.02139907.629298.89669937.214295.36099960.225294.47589976.661291.6932
 9989.81291.115510016.11292.181910029.26 293.47510042.41293.198510055.55293.8086
10065.42293.5393 10068.7294.452910101.58297.078710104.86297.009810118.01299.1463
10127.87299.686310131.16300.576310141.02301.840910160.75306.125310187.04308.7832
10210.05313.284110219.92315.888210242.93323.603410256.08326.662810264.37330.2221
#Mann= 3 , 0 , 0
9819.063  0.1119       09819.063  0.1119       010264.37  0.1119       0
#XS Ineff= 2 , 0
       0                               0
Bank Sta=9819.063,10264.37
Exp/Cntr=0.3,0.1

Type RM Length L Ch R = 1 ,10569.68,234.239400,234.239400,234.239400
XS GIS Cut Line= 2
1242053.80007908 626809.811660291241619.77230132626905.297771409
#Sta/Elev= 30
9785.554313.00989790.511311.83599810.667 305.8469824.104302.62539847.619298.6717
9867.775294.31279877.852292.9783 9887.93290.79269898.008289.26059918.164287.5568
 9934.96286.97199948.398287.38499961.835286.78979971.913287.56219975.272287.5001
9998.787284.161810008.86284.6754 10022.3284.788710035.74286.426110045.82286.1747
10052.54 286.45910076.05289.497510096.21293.5595   10113294.756110153.31303.0385
10170.11308.187910180.19310.436910196.99 315.712 10220.5321.861110229.96323.9514
#Mann= 3 , 0 , 0
9785.554  0.1023       09785.554  0.1023       010229.96  0.1023       0
#XS Ineff= 2 , 0
       0                               0
Bank Sta=9785.554,10229.96
Exp/Cntr=0.3,0.1

Type RM Length L Ch R = 1 ,10335.44,212.213300,212.213300,212.213300
XS GIS Cut Line= 2
 1241966.9945235626532.0338825291241553.80007908 626762.93666029
#Sta/Elev= 30
9748.164314.52029767.312308.1061 9793.33298.37549797.088297.96199804.605 298.107
9808.363296.93289812.121294.7669 9815.88 293.2299830.913 291.2649845.947289.7255
9872.255288.78329876.014287.8227 9883.53284.99289891.047282.96589898.564279.5458
9909.839278.46289921.114278.36419936.147277.41729943.664277.71329981.248276.4868
9989.253275.535910000.04275.164410022.59276.688210045.14279.647710063.93282.8451
   10094287.136710142.86297.789810195.47 311.24210210.51314.5165 10221.5317.7861
#Mann= 3 , 0 , 0
9748.164  0.1043       09748.164  0.1043       0 10221.5  0.1043       0
#XS Ineff= 2 , 0
       0                               0
Bank Sta=9748.164,10221.5
Exp/Cntr=0.3,0.1

Type RM Length L Ch R = 1 ,10123.23,120.490100,120.490100,120.490100
XS GIS Cut Line= 6
1241910.02869826626339.7060601571241758.89465152626421.953879287
1241620.08165176626485.3305534361241578.57871892626506.335179588
1241515.25190621626544.0670126881241428.11235357626601.508983643
#Sta/Elev= 30
9725.357328.10329735.437322.78779772.622305.27539783.828297.64219791.298293.9181
9802.504291.57679813.709290.3203 9838.39284.65049873.472280.96019903.206274.9002
9917.774 274.7689950.547270.4709 9979.24268.23839997.173267.289310007.94267.8408
10015.12266.617710033.08267.077710047.44269.028110065.77269.766310084.15 271.341
10091.51272.502810102.77275.230110114.22275.367810126.55276.450310133.32277.6914
10160.05279.368410183.26282.386110201.14283.123910224.98287.886110274.64292.7505
#Mann= 3 , 0 , 0
9725.357  0.0662       09725.357  0.0662       010274.64  0.0662       0
#XS Ineff= 2 , 0
       0                               0
Bank Sta=9725.357,10274.64
Exp/Cntr=0.3,0.1

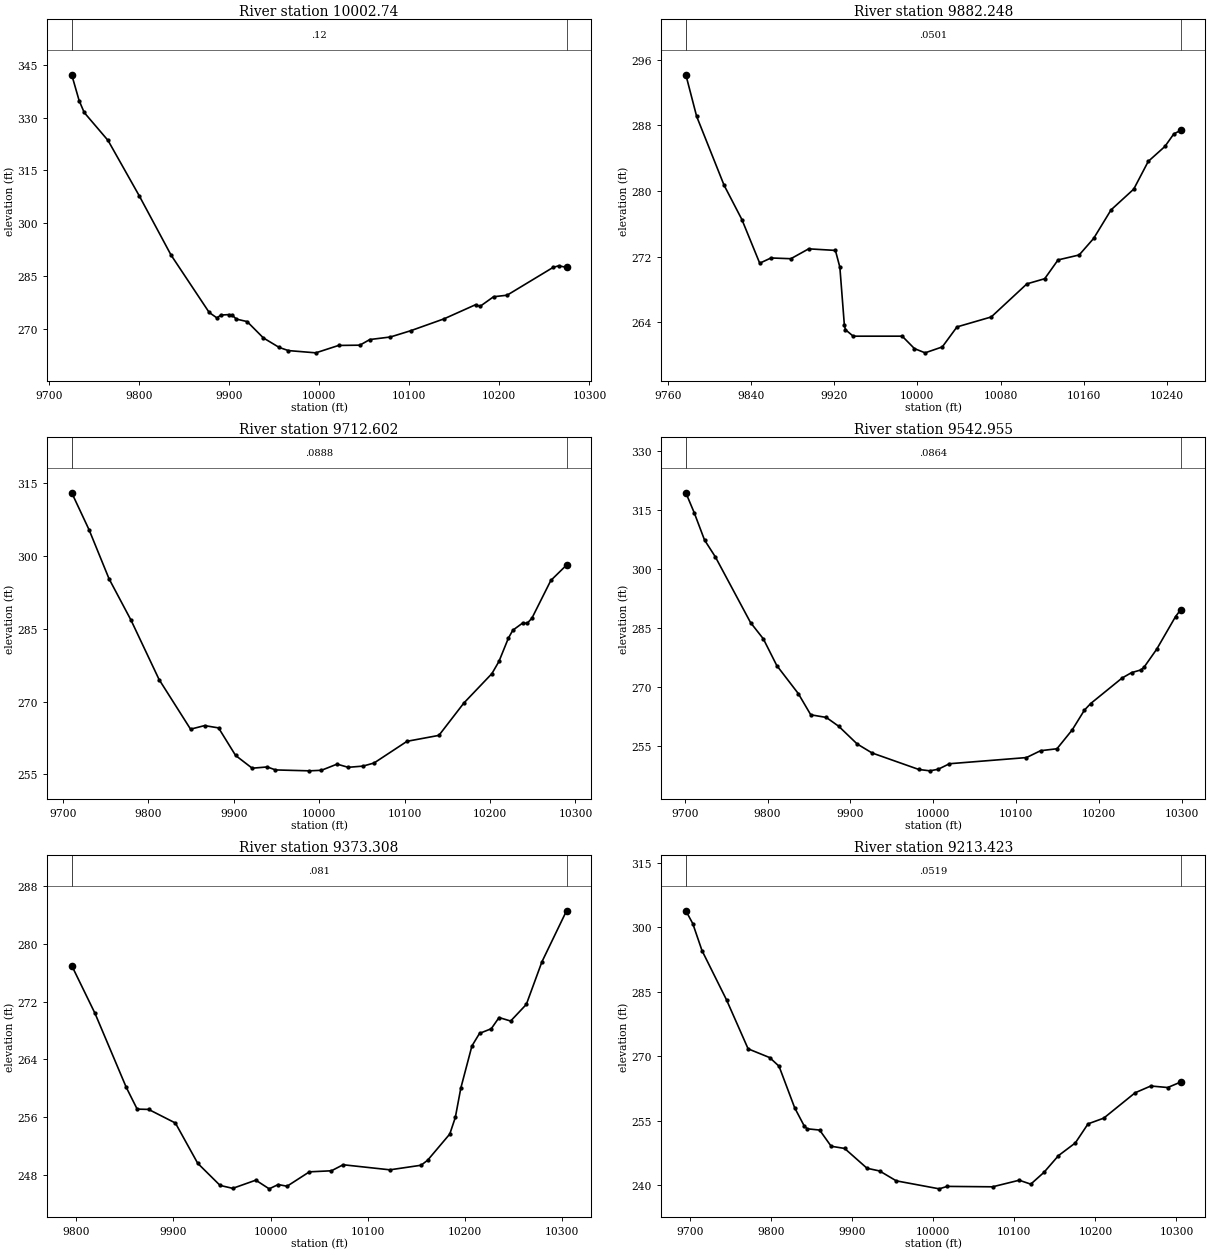
Type RM Length L Ch R = 1 ,10002.74,120.490100,120.490100,120.490100
XS GIS Cut Line= 6
1241822.52854473626188.8368136851241721.30419824626264.238768589
1241597.08361616626368.6864642681241496.17712299626466.465742117
1241445.06200877626510.8768974651241404.03418902 626543.61386278
#Sta/Elev= 30
9725.368342.19719733.566334.87659739.205331.4682 9765.64323.52869800.393307.7373
9835.583290.92759877.949274.59219886.541273.03629890.838273.8462 9899.43273.9751
9903.727273.77539908.023272.71199920.062 271.9969938.097267.34829955.633264.6445
9965.796263.74819996.285263.104210021.62265.208810045.19265.284210056.25266.8865
 10079.1267.613610101.77269.408510138.49  272.7610173.59276.789710178.59276.3192
 10193.6279.058410208.61279.497210259.62287.394710265.77287.860510274.62287.4204
#Mann= 3 , 0 , 0
9725.368    0.12       09725.368    0.12       010274.62    0.12       0
#XS Ineff= 2 , 0
       0                               0
Bank Sta=9725.368,10274.62
Exp/Cntr=0.3,0.1

Type RM Length L Ch R = 1 ,9882.248,169.646500,169.646500,169.646500
XS GIS Cut Line= 2
1241673.59174573626163.9783269611241309.00841242626469.533882529
#Sta/Elev= 30
9777.489294.1685 9787.86289.09879814.251280.69539831.374276.51129848.497271.1885
9859.367271.82549878.462271.73469895.585 272.9399921.269272.7465 9925.55270.6942
 9929.83263.70939930.875263.08029938.392262.2851 9985.48262.28739997.274260.7691
10007.49260.254310024.01260.976210038.14263.417410071.09264.631210105.34268.6656
10122.46269.2945 10135.3271.587310155.61272.191710169.55274.215510186.26277.6912
10208.08280.224110222.01283.605210238.04285.4278 10246.6286.959710253.18 287.385
#Mann= 3 , 0 , 0
9777.489  0.0501       09777.489  0.0501       010253.18  0.0501       0
#XS Ineff= 2 , 0
       0                               0
Bank Sta=9777.489,10253.18
Exp/Cntr=0.3,0.1

Type RM Length L Ch R = 1 ,9712.602,169.646500,169.646500,169.646500
XS GIS Cut Line= 6
1241622.33631695626006.6981822221241453.11448433626133.059120456
1241416.57803548626163.4696514231241380.49463241626199.051551635
1241328.23468685626244.0045310871241168.33646964626365.312204905
#Sta/Elev= 30
9710.464313.02939730.794305.39729754.165 295.3049779.929286.76069812.686274.5638
9849.537264.33239865.916265.06799882.294264.59849902.218258.92479921.658256.2942
9939.376 256.5559948.919255.93879988.648255.751410002.68 255.86410020.98257.1354
10033.96256.478810051.27256.723810064.26257.364510102.86261.835110140.18263.0566
10169.36269.716210202.18275.775310210.43278.285310221.47283.081110226.66284.7126
10238.03286.180710243.54286.145710249.06287.210910271.14294.965910289.55298.1392
#Mann= 3 , 0 , 0
9710.464  0.0888       09710.464  0.0888       010289.55  0.0888       0
#XS Ineff= 2 , 0
       0                               0
Bank Sta=9710.464,10289.55
Exp/Cntr=0.3,0.1

Type RM Length L Ch R = 1 ,9542.955,169.646500,169.646500,169.646500
XS GIS Cut Line= 6
1241580.59952775625909.4327847031241406.87230492626012.785782413
1241356.63003033626035.1717144841241293.49897958626051.845000889
1241230.98382611626077.9154781781241049.51805704626177.597512942
#Sta/Elev= 30
9701.284319.39639711.356314.3555 9723.82307.41529736.954303.10569779.402286.4472
9794.837282.31669811.069 275.5389837.073268.41459852.074263.03769870.826262.3655
9885.827260.12619908.125255.62719926.083253.34759982.507249.15719995.919248.8073
10006.01249.214910019.56250.6121 10112.5252.175210129.56253.919510149.34254.4106
10167.76259.203410182.49 264.21710190.04265.891110227.99272.372310239.38273.7378
10250.76  274.4310254.56275.135210269.74279.683710292.51287.9699 10298.7 289.705
#Mann= 3 , 0 , 0
9701.284  0.0864       09701.284  0.0864       0 10298.7  0.0864       0
#XS Ineff= 2 , 0
       0                               0
Bank Sta=9701.284,10298.7
Exp/Cntr=0.3,0.1

Type RM Length L Ch R = 1 ,9373.308,159.885200,159.885200,159.885200
XS GIS Cut Line= 3
1241383.66119018625755.9922158571241194.42507902625941.756104723
1240994.77230129626082.381104752
#Sta/Elev= 30
9795.318276.98739819.302270.36979851.484260.13439862.688257.13139874.471257.0919
9902.056255.20749925.043249.6333 9948.03246.57959961.038246.1725 9984.81247.3033
9998.602246.104810007.87246.698710016.99246.465310039.98248.456710062.65248.6012
10074.69249.436410122.85248.735210154.95249.3683 10161.7250.063210184.49253.6853
10190.19 255.97910195.89260.060210207.28265.864810215.14267.608610227.18268.2487
10235.21269.798310247.16269.3148 10263.3271.617610279.35277.5072 10304.7284.5653
#Mann= 3 , 0 , 0
9795.318   0.081       09795.318   0.081       0 10304.7   0.081       0
#XS Ineff= 2 , 0
       0                               0
Bank Sta=9795.318,10304.7
Exp/Cntr=0.3,0.1

Type RM Length L Ch R = 1 ,9213.423,159.885200,159.885200,159.885200
XS GIS Cut Line= 6
1241393.62148451625613.0242122521241304.42339091625664.834715154
1241222.56084786625715.2630401971241184.80044439625740.877358553
1241050.32748087  625838.87646471240882.55134034625946.198827738
#Sta/Elev= 30
9694.746 303.8849703.294300.89799714.676294.60789745.029283.08779771.588271.7103
9798.151269.67679809.711267.66659828.978257.99169840.538253.83269844.392253.0824
9859.805252.78529874.026249.01249890.632248.50219918.285243.88279933.785243.2529
9954.406240.949110007.38239.088310017.13239.657610073.15239.561210106.08 241.097
10120.29240.179910136.62242.934810154.51246.832910175.29249.787210190.95254.2286
10210.31255.559910249.03261.473210268.39263.053310289.25262.697810305.25263.9722
#Mann= 3 , 0 , 0
9694.746  0.0519       09694.746  0.0519       010305.25  0.0519       0
#XS Ineff= 2 , 0
       0                               0
Bank Sta=9694.746,10305.25
Exp/Cntr=0.3,0.1

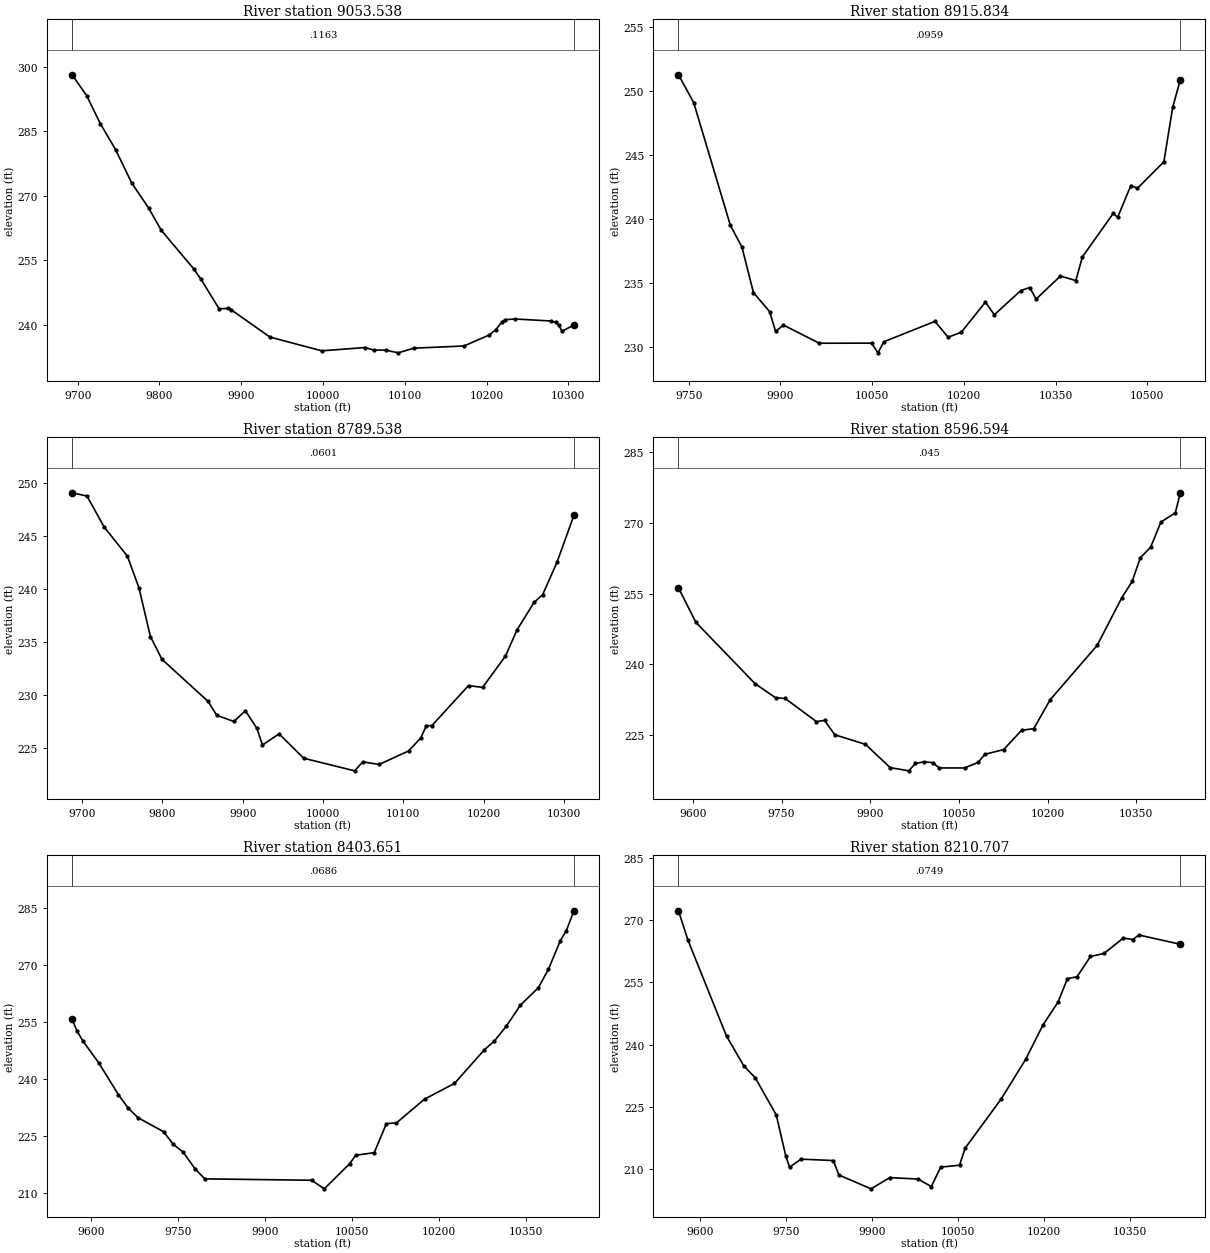
Type RM Length L Ch R = 1 ,9053.538,137.703900,137.703900,137.703900
XS GIS Cut Line= 6
1241347.71551896625496.115844507 1241147.3835706 625602.78621177
1241102.82025701 625621.960483361241043.36614115625642.427492876
1241005.96024221 625660.004375151240806.26743225625782.222818586
#Sta/Elev= 30
9693.068298.20859710.958293.32929727.616286.82869746.269280.76839766.098272.9705
9786.775  267.149802.227261.95999841.915252.97889850.725250.56439872.923243.6717
9883.966243.77459887.648 243.4529935.043237.09699998.413233.884710051.36234.6521
10062.23234.065510076.91234.043110092.05 233.41610110.97234.5022 10172.5235.0142
10203.42237.585510211.15238.787510218.89240.602710222.75241.126610234.35241.3108
10278.32240.8404 10284.6240.546710288.47239.834110292.33238.474210306.92239.8642
#Mann= 3 , 0 , 0
9693.068  0.1163       09693.068  0.1163       010306.92  0.1163       0
#XS Ineff= 2 , 0
       0                               0
Bank Sta=9693.068,10306.92
Exp/Cntr=0.3,0.1

Type RM Length L Ch R = 1 ,8915.834,126.296100,126.296100,126.296100
XS GIS Cut Line= 4
1241194.42299238625364.4365601391241081.01028204625428.589204371
1240878.24210295625643.9587957111240518.52906212625806.631572142
#Sta/Elev= 30
9733.243251.24159758.107 249.0799818.192239.49819837.039  237.829855.886234.2685
9882.367232.7858 9892.11231.24039904.898231.74229963.477230.324610049.09230.3304
10059.62229.5753 10069.2230.440310152.73232.028610174.34230.792510195.95231.1824
10235.25233.524210249.96 232.54310293.17234.428410307.57234.663810318.37233.7702
10357.98235.558310383.18235.207510393.99237.0547 10444.4240.4386 10451.6240.1396
 10473.2242.6107   10484242.393810527.21244.459710541.61 248.69610554.13250.8607
#Mann= 3 , 0 , 0
9733.243  0.0959       09733.243  0.0959       010554.13  0.0959       0
#XS Ineff= 2 , 0
       0                               0
Bank Sta=9733.243,10554.13
Exp/Cntr=0.3,0.1

Type RM Length L Ch R = 1 ,8789.538,192.943700,192.943700,192.943700
XS GIS Cut Line= 6
1241199.72806288625324.8944898081240980.27778365625421.486195031
1240946.97402045625432.0370683551240811.51312511 625463.38465172
1240722.66009914625496.4414849451240615.43882211625541.758885031
#Sta/Elev= 30
9687.451249.06519705.976248.75949727.541245.82079756.295243.08529770.673 240.114
 9785.05235.48749799.427233.33589856.935229.35669867.718228.04389889.089227.4688
9903.303228.49039917.516226.83559924.623225.24689945.354226.29559975.922 223.997
10039.43222.806310049.56 223.65410070.03223.410710106.71224.689210121.73225.9093
10128.73227.061710135.73227.087810181.24230.855310198.78 230.68710227.28233.6422
10241.53236.0961 10262.9238.713610273.58239.445110291.39242.484910312.54246.9393
#Mann= 3 , 0 , 0
9687.451  0.0601       09687.451  0.0601       010312.54  0.0601       0
#XS Ineff= 2 , 0
       0                               0
Bank Sta=9687.451,10312.54
Exp/Cntr=0.3,0.1

Type RM Length L Ch R = 1 ,8596.594,192.943600,192.943600,192.943600
XS GIS Cut Line= 6
1241289.28989786625109.655744501 1240962.3510436625218.579911111
1240920.00291496 625234.862603911240839.33390129625273.136526119
1240652.37357336625332.9797628131240489.15670182  625390.7711462
#Sta/Elev= 30
 9575.61256.2576 9604.84248.95539705.126235.91779739.707232.92999756.099232.7703
9808.869227.87269822.702 228.1179839.993225.07689891.864223.03869933.578218.1074
9965.213  217.429976.174218.9823 9990.81219.332810005.47219.167310016.55218.0319
10059.42218.031210082.47219.213310093.87 220.92810125.52221.924410155.88226.0024
10176.55 226.37610204.11232.472910283.67244.025110325.43254.141110342.84257.5847
10356.76262.622910374.16264.860910391.56270.194710415.93272.150810424.38276.4032
#Mann= 3 , 0 , 0
 9575.61   0.045       0 9575.61   0.045       010424.38   0.045       0
#XS Ineff= 2 , 0
       0                               0
Bank Sta=9575.61,10424.38
Exp/Cntr=0.3,0.1

Type RM Length L Ch R = 1 ,8403.651,192.943600,192.943600,192.943600
XS GIS Cut Line= 6
1241217.29577047624957.8398401551240902.01609343625040.951424629
1240845.31531609625061.7268551371240767.09283972625099.510197073
1240716.35658484625119.8023395991240396.01559522625221.488456532
#Sta/Elev= 30
9567.966255.72969576.459252.61369586.615249.96369613.699244.26919647.553235.8609
 9664.48232.28979681.407229.75259725.417226.05369742.345222.71899759.272220.6552
9779.584216.27169796.511213.6071 9980.39213.233710002.22210.973810045.85217.6036
10056.45 219.83610088.25220.520110109.18228.186710126.49228.363210174.82234.6438
10226.39238.777310277.96247.680310295.15249.979810315.78253.923610339.85259.4215
10370.79264.027910387.98268.844110408.61276.437310418.92279.060510432.05284.3368
#Mann= 3 , 0 , 0
9567.966  0.0686       09567.966  0.0686       010432.05  0.0686       0
#XS Ineff= 2 , 0
       0                               0
Bank Sta=9567.966,10432.05
Exp/Cntr=0.3,0.1

Type RM Length L Ch R = 1 ,8210.707,192.943700,192.943700,192.943700
XS GIS Cut Line= 6
1241222.09766299624838.8733846951240943.86822985624887.091520035
1240709.20040391624892.2357745071240603.35690867624901.942687916
1240493.54578194624921.7074791271240358.28860126624955.942723162
#Sta/Elev= 30
9562.605272.25489579.293265.11539646.383 242.0529676.417234.9056 9696.44232.0294
9733.102223.05269749.659213.19029756.281210.47629776.149212.4169 9832.44212.0829
9842.373208.5915 9898.27205.26619931.138207.98369980.356207.609110003.32205.8051
10019.73210.500310052.53210.959710062.38215.076910124.81226.842210167.72236.4332
10197.51244.6206 10224.1250.235610240.72255.904510257.41256.368910280.84261.2499
10304.31261.9666   10338265.681610354.85265.3342   10365266.417810437.42264.1895
#Mann= 3 , 0 , 0
9562.605  0.0749       09562.605  0.0749       010437.42  0.0749       0
#XS Ineff= 2 , 0
       0                               0
Bank Sta=9562.605,10437.42
Exp/Cntr=0.3,0.1

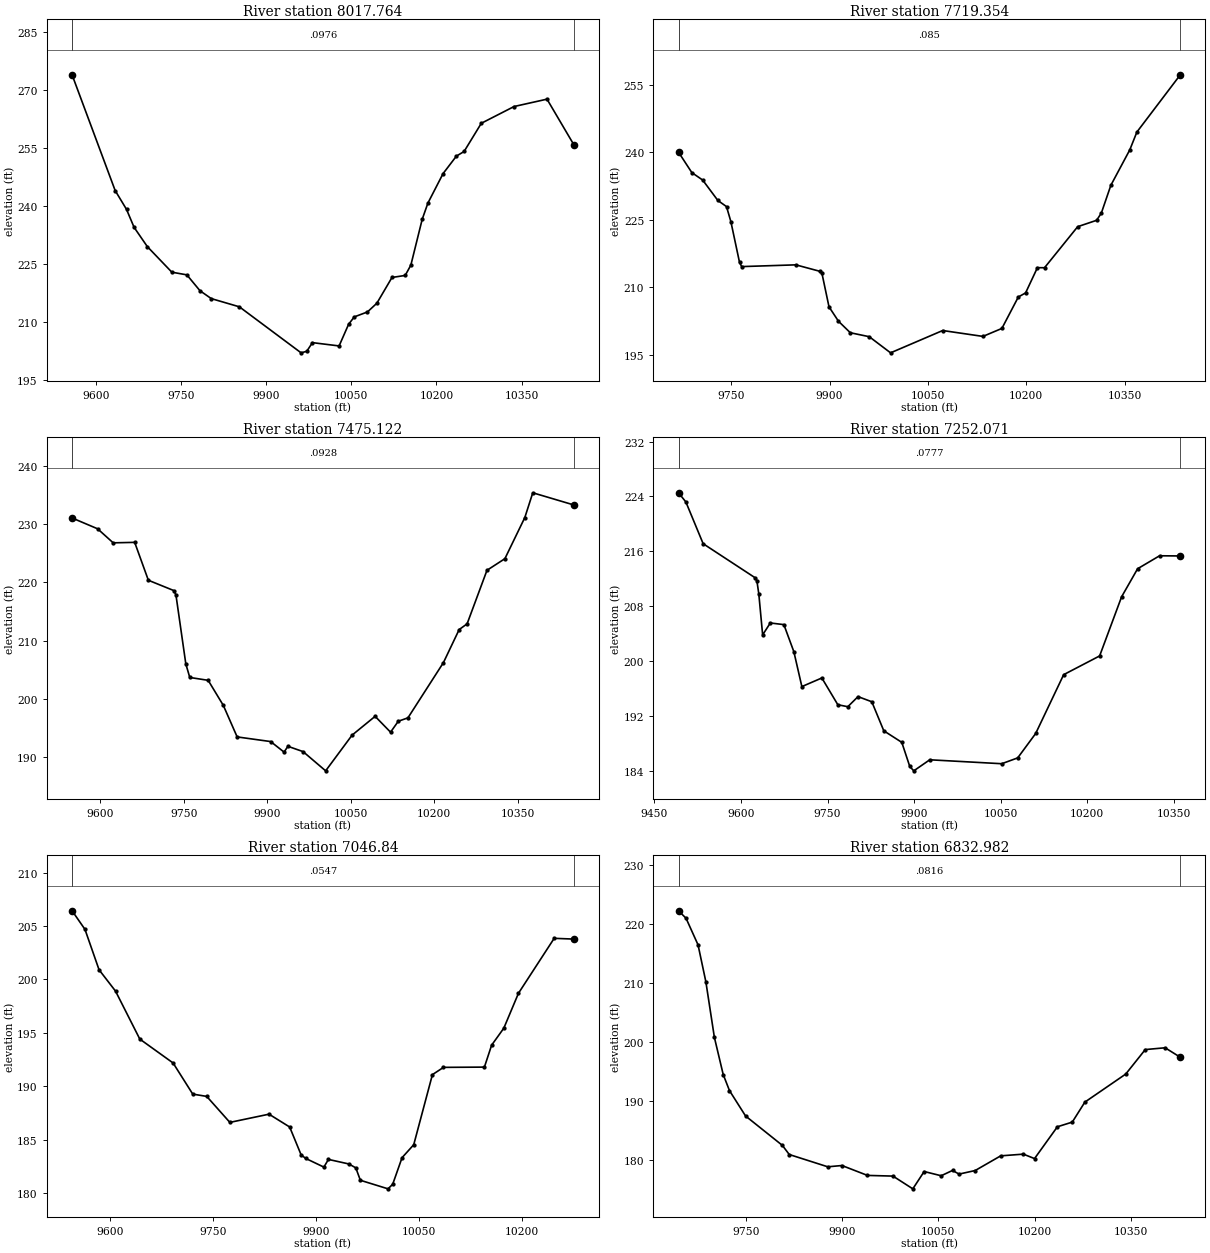
Type RM Length L Ch R = 1 ,8017.764,298.409900,298.409900,298.409900
XS GIS Cut Line= 6
1241211.23544179624634.9774943811241047.48941829624666.415982696
1240808.04078951624693.8246739911240606.67866635624730.627956895
1240479.46675184 624759.329923661240343.31971685624798.198055977
#Sta/Elev= 30
9557.724 273.993 9633.67244.06799653.694239.20049667.019234.56269690.339229.5806
9733.589222.95859760.073222.26629783.247218.1584 9803.11216.1302 9852.65214.0052
9961.462202.1075 9971.44202.51269981.477204.745610028.45203.891510045.18209.4801
10055.16211.399310078.44212.679110095.07214.943210121.68221.594410144.97222.1173
10154.95224.784310174.94236.625310184.99240.820110211.78248.4575 10235.3252.9763
 10248.8254.162210279.16261.456110336.93265.788810394.93267.690410442.29255.8981
#Mann= 3 , 0 , 0
9557.724  0.0976       09557.724  0.0976       010442.29  0.0976       0
#XS Ineff= 2 , 0
       0                               0
Bank Sta=9557.724,10442.29
Exp/Cntr=0.3,0.1

Type RM Length L Ch R = 1 ,7719.354,244.232000,244.232000,244.232000
XS GIS Cut Line= 3
1241052.06396794 624348.87416029 1240835.9181346624374.915826976
1240338.52230129624604.082493618
#Sta/Elev= 30
9669.703240.02259690.012235.48219706.535 233.8289729.667229.29269742.885227.9227
9749.494224.60649762.712215.53089766.017 214.5819848.631214.97119884.981213.5455
9888.367213.12959899.204205.63439913.653202.42779931.715199.87089960.613198.9893
9993.124195.401410072.59200.3639   10134199.0564 10162.9200.832410187.99207.8286
10199.03 208.72510217.09214.344610227.92214.3285 10278.5 223.45910307.39224.8771
10314.62 226.49710329.12232.669210357.97240.5405 10368.8244.505410435.06257.2418
#Mann= 3 , 0 , 0
9669.703   0.085       09669.703   0.085       010435.06   0.085       0
#XS Ineff= 2 , 0
       0                               0
Bank Sta=9669.703,10435.06
Exp/Cntr=0.3,0.1

Type RM Length L Ch R = 1 ,7475.122,223.051000,223.051000,223.051000
XS GIS Cut Line= 6
1241015.65935879624086.469013129 1240883.3962643624136.791338489
1240686.57760356 624217.54060506  1240529.871334624260.630356681
 1240448.8754266624288.4075442061240173.54486233624405.340849089
#Sta/Elev= 30
9549.201231.04869595.009229.19599623.092226.78089661.705 226.8639686.277220.3579
9732.332218.57429735.878217.82059753.609205.98169760.702203.67089793.731203.1764
9820.988198.87149845.811193.4623 9906.02192.66489930.122190.85599937.009191.8496
 9964.21190.943510004.82187.638910052.37193.771710093.71196.995210121.45 194.274
10135.33196.152610152.69196.736810216.46206.221910244.72211.893410258.98212.8734
10294.69222.066310326.89224.061510362.68 231.12210376.99235.3746 10450.8233.2822
#Mann= 3 , 0 , 0
9549.201  0.0928       09549.201  0.0928       0 10450.8  0.0928       0
#XS Ineff= 2 , 0
       0                               0
Bank Sta=9549.201,10450.8
Exp/Cntr=0.3,0.1

Type RM Length L Ch R = 1 ,7252.071,205.230800,205.230800,205.230800
XS GIS Cut Line= 3
1241018.20980132623900.9574936331240843.73063463623929.603326961
1240187.48063463624150.957493618
#Sta/Elev= 30
 9491.87 224.5339504.594223.19069534.517217.10149624.285212.1503 9627.61211.7078
9630.935 209.7869637.584203.80069650.883205.53889674.383205.29739691.695  201.34
9705.545196.2571 9740.17197.51479767.869193.60839785.181193.32179802.844194.7939
9826.731194.04449847.505189.80529878.667188.12229892.517184.60239899.442183.9654
9927.141185.577410051.79185.003510079.49185.854610110.65 189.41510159.12197.9958
10221.45200.729310259.54 209.36110287.24213.450110325.32215.342510361.26215.3159
#Mann= 3 , 0 , 0
 9491.87  0.0777       0 9491.87  0.0777       010361.26  0.0777       0
#XS Ineff= 2 , 0
       0                               0
Bank Sta=9491.87,10361.26
Exp/Cntr=0.3,0.1

Type RM Length L Ch R = 1 , 7046.84,213.857800,213.857800,213.857800
XS GIS Cut Line= 6
1240879.28110015623750.3104026761240677.80533552623808.196213782
 1240455.5765667623849.6132242381240334.90981337623882.513329521
1240224.12495035623926.2076158521240181.24523997623954.742441639
#Sta/Elev= 30
9544.315206.43149563.104204.69119583.671 200.9029607.665198.90659643.064194.4111
 9691.57192.17339720.244189.25739740.624 189.0429774.352186.60679831.428187.3764
9861.531186.17499878.153183.57689884.802183.23429911.399182.41879918.048183.1387
9947.969182.71069957.942182.34529964.591181.184310004.94180.382110011.75180.8154
10025.37183.303610042.39184.515510069.62191.080110085.77191.761710145.42191.7862
10155.92193.839210173.72195.434610195.08198.705510247.13203.850510275.82203.7796
#Mann= 3 , 0 , 0
9544.315  0.0547       09544.315  0.0547       010275.82  0.0547       0
#XS Ineff= 2 , 0
       0                               0
Bank Sta=9544.315,10275.82
Exp/Cntr=0.3,0.1

Type RM Length L Ch R = 1 ,6832.982,178.724300,178.724300,178.724300
XS GIS Cut Line= 2
1240719.06408343623410.7887824621240138.30153006623934.293055966
#Sta/Elev= 30
 9645.13222.29089656.823221.02349675.532216.51389687.742210.23739700.993 200.821
9714.733194.52789724.534191.79279749.581187.49369807.002182.50279817.636180.9634
9877.674178.87869899.759179.09639939.512177.41889979.265177.303110010.18175.1423
10027.85178.078710054.35177.361410072.02178.261310082.24177.643210107.36178.2469
10147.11180.735110182.45181.025310199.84180.272810235.45185.666510258.65186.4573
10278.25189.847410341.95194.604910372.38198.7564 10403.3199.060310427.01197.4502
#Mann= 3 , 0 , 0
 9645.13  0.0816       0 9645.13  0.0816       010427.01  0.0816       0
#XS Ineff= 2 , 0
       0                               0
Bank Sta=9645.13,10427.01
Exp/Cntr=0.3,0.1