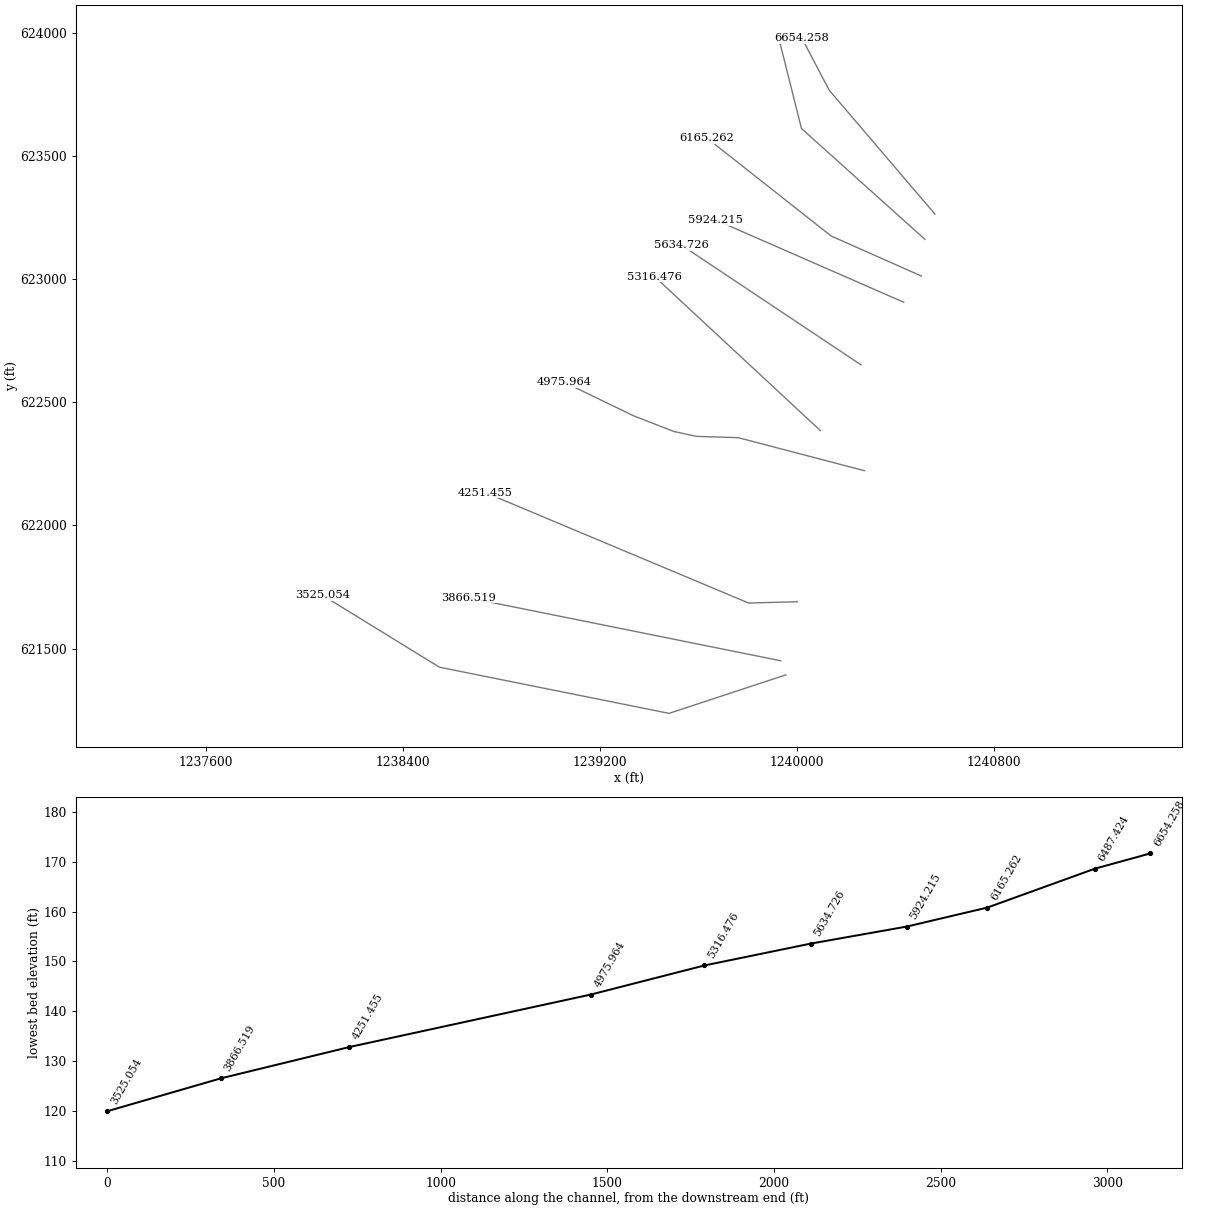
HEC-RAS study 335_ras.prj: 335

--- 335_ras.g01 (geometry) --- (continued)

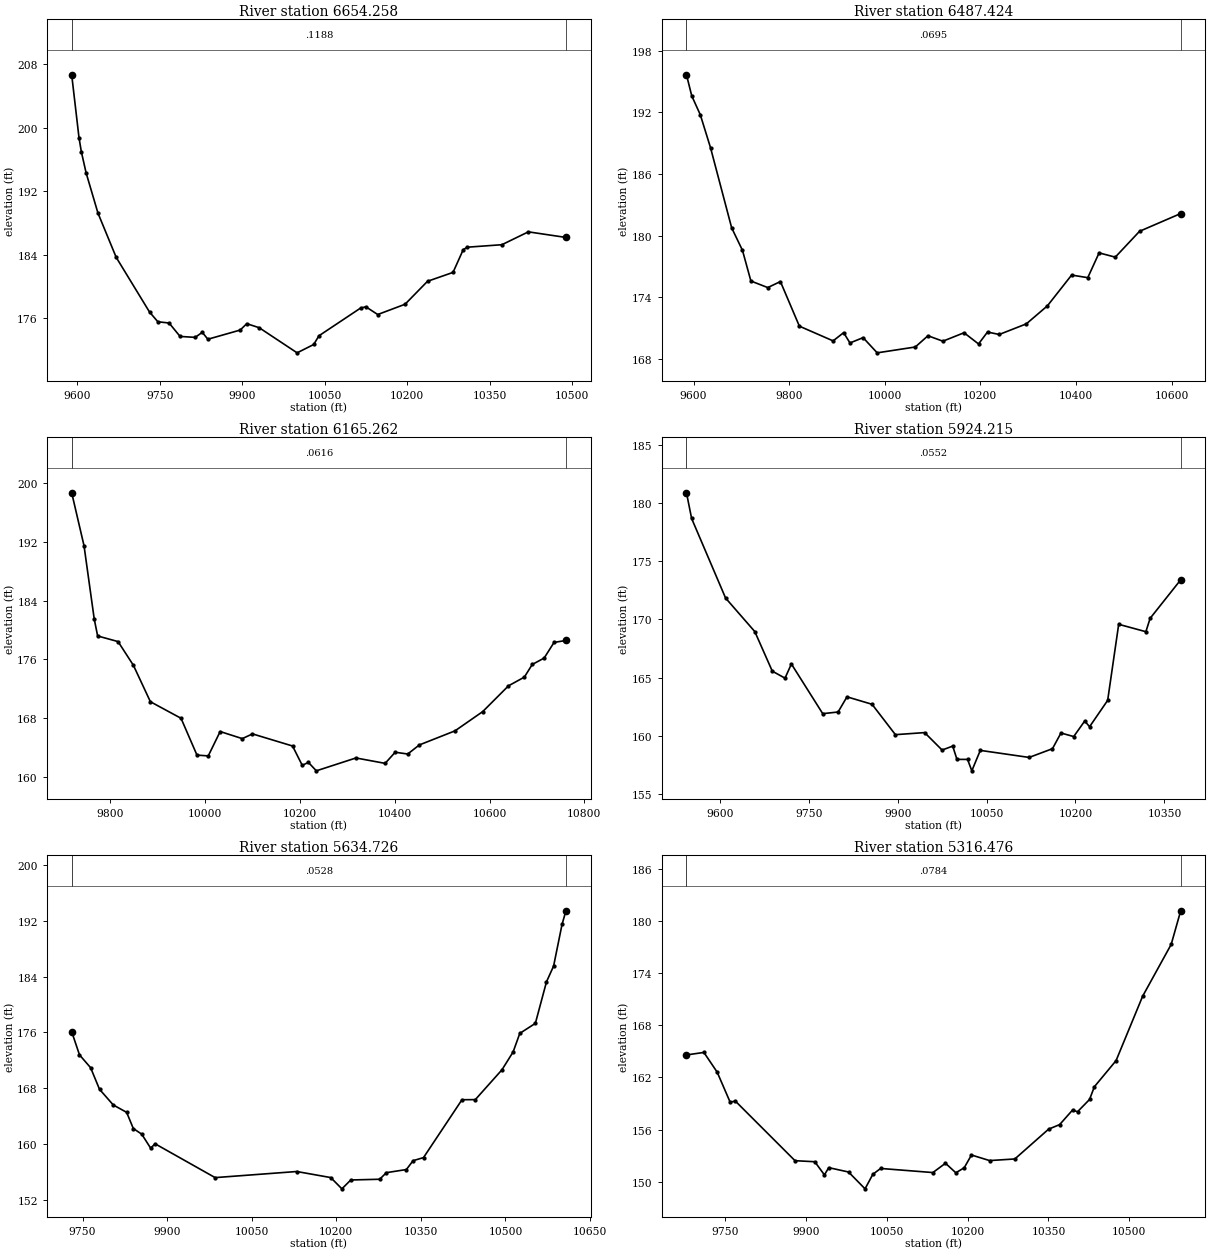
Type RM Length L Ch R = 1 ,6654.258,166.833500,166.833500,166.833500
XS GIS Cut Line= 3
1240559.55887514 623263.553205521240130.12177581623766.608093351
1240019.69509307623977.236765906
#Sta/Elev= 30
9589.771206.69549603.065198.77159607.379 196.9839616.006194.33499637.575189.2637
9670.773183.68629731.411176.79839746.571175.57079766.985175.41619786.996173.7233
9814.436173.60589827.377174.24279837.528173.37019896.395174.52819908.272175.3319
9930.905174.82459999.924171.656710030.12172.708610039.65173.806710115.45177.3014
10125.02177.458510146.59176.4836 10196.3177.779310237.18180.672310283.61181.7939
10302.13184.651610309.54184.969210372.51185.281810420.67186.902510489.01186.1987
#Mann= 3 , 0 , 0
9589.771  0.1188       09589.771  0.1188       010489.01  0.1188       0
#XS Ineff= 2 , 0
       0                               0
Bank Sta=9589.771,10489.01
Exp/Cntr=0.3,0.1

Type RM Length L Ch R = 1 ,6487.424,322.162400,322.162400,322.162400
XS GIS Cut Line= 3
1240518.66010374623161.306277126 1240017.6501545623611.192762166
1239929.71779606623960.877257332
#Sta/Elev= 30
9585.263195.66139596.296193.60729614.206191.7675 9635.58188.55789679.774180.7617
9702.395178.56969720.033175.58179755.308 174.9439781.765175.5285 9821.45171.1854
9892.001169.75339914.048170.55339927.276169.55149954.763170.06849984.226168.5889
10063.97169.157410090.43170.252310121.72169.722510165.91170.544610196.25169.4552
10215.02170.613610239.57 170.37710296.24171.409610340.22173.159610390.96176.1596
10424.79175.908310448.48178.3225 10482.3177.904610533.05180.421810619.19182.1516
#Mann= 3 , 0 , 0
9585.263  0.0695       09585.263  0.0695       010619.19  0.0695       0
#XS Ineff= 2 , 0
       0                10247.42       0
Bank Sta=9585.263,10619.19
Exp/Cntr=0.3,0.1

Type RM Length L Ch R = 1 ,6165.262,241.046400,241.046400,241.046400
XS GIS Cut Line= 3
 1240504.5124675623012.2761622521240137.75899532623175.036578938
1239634.28677309 623572.17199558
#Sta/Elev= 30
9718.628 198.7159744.658191.49019766.194181.49239773.373179.19149816.446178.4259
 9848.75175.19829884.644170.22659949.253167.96879982.877162.949510006.68162.8391
10031.81166.161410078.47165.195610100.01165.8398 10184.5 164.18910204.96161.5519
10217.93161.956610234.64160.803510318.21162.559210379.78 161.82210400.97163.3391
10427.46163.097510451.93164.334610527.15166.254710585.65168.881410639.97172.3951
 10673.4173.579510690.11175.306510715.19176.179610736.08178.311410761.12178.5803
#Mann= 3 , 0 , 0
9718.628  0.0616       09718.628  0.0616       010761.12  0.0616       0
#XS Ineff= 2 , 0
       0                10325.34       0
Bank Sta=9718.628,10761.12
Exp/Cntr=0.3,0.1

Type RM Length L Ch R = 1 ,5924.215,289.489400,289.489400,289.489400
XS GIS Cut Line= 2
1240432.89788422  622905.93935671239669.00899532623240.140745595
#Sta/Elev= 30
9543.708180.86979552.388178.66449609.685171.83419658.981168.95599688.469165.5617
9709.955164.95819720.699166.17629773.575161.91239799.482162.05359814.502163.3572
 9856.78162.71629896.172160.10949945.467160.28699974.955158.78939992.861159.1276
10000.02157.989110017.93157.984910025.09157.004610039.41158.760110121.78 158.155
10161.17 158.905 10175.5160.252310196.98159.946610215.58161.280510223.77160.7907
10254.28163.053210272.88169.581410318.74168.9466 10325.9170.0934 10377.5173.4013
#Mann= 3 , 0 , 0
9543.708  0.0552       09543.708  0.0552       0 10377.5  0.0552       0
#XS Ineff= 2 , 0
       0                10083.54       0
Bank Sta=9543.708,10377.5
Exp/Cntr=0.3,0.1

Type RM Length L Ch R = 1 ,5634.726,318.250400,318.250400,318.250400
XS GIS Cut Line= 2
1240259.28677309622652.0331067141239530.12010643623138.144217804
#Sta/Elev= 30
9730.811176.11459744.639172.78569764.354170.94759780.127167.85029804.587165.5968
9828.246164.54299840.075162.22519855.045161.40739870.817 159.4049878.703160.0312
9985.166  155.1810129.89156.055110190.21155.185510209.92153.569810225.69154.8395
10276.95 154.94610288.78 155.89110324.27 156.337 10336.1157.606210354.65158.0534
10422.85166.350610446.51166.368510493.82170.653310513.54173.209710525.37  175.87
10552.97177.306410572.68183.258310585.32185.526810600.29191.501110607.16 193.456
#Mann= 3 , 0 , 0
9730.811  0.0528       09730.811  0.0528       010607.16  0.0528       0
#XS Ineff= 2 , 0
       0                10165.55       0
Bank Sta=9730.811,10607.16
Exp/Cntr=0.3,0.1

Type RM Length L Ch R = 1 ,5316.476,340.511400,340.511400,340.511400
XS GIS Cut Line= 2
 1240094.3562175622385.1060233861239421.61316198623010.106023386
#Sta/Elev= 30
 9677.57 164.5859709.974164.87159734.609162.6067 9758.71159.15529768.351159.2842
9879.217152.43259915.971152.31279933.883150.8007 9941.88151.63289978.665151.1329
10009.36149.198110023.82150.868510038.29151.5412 10135.4151.069210158.79152.1384
10178.07151.041510193.62151.621910207.05153.085910240.74152.445610287.66152.6306
10350.35156.054810370.88156.578210394.99158.258810404.09158.054110426.48159.4688
10435.44160.932810475.74163.931410525.13171.334610578.16177.285810595.83 181.149
#Mann= 3 , 0 , 0
 9677.57  0.0784       0 9677.57  0.0784       010595.83  0.0784       0
#XS Ineff= 2 , 0
       0                10152.64       0
Bank Sta=9677.57,10595.83
Exp/Cntr=0.3,0.1

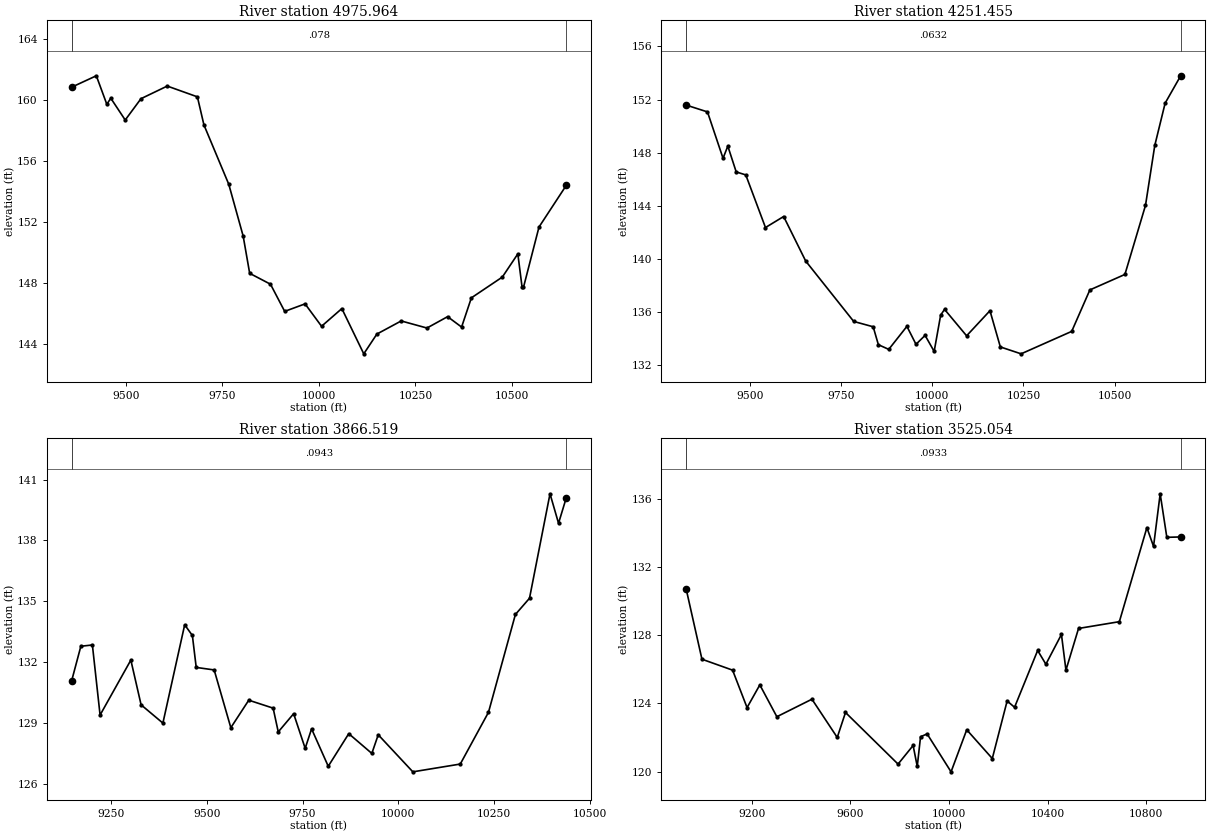
Type RM Length L Ch R = 1 ,4975.964,724.509100,724.509100,724.509100
XS GIS Cut Line= 6
1240273.18029881 622222.307545771239761.59015741622356.280106192
1239591.00995455622361.7016688881239499.40506207622381.645650267
1239336.63679677622444.9079852871239055.93301571622580.637186746
#Sta/Elev= 30
9359.704160.83919423.451 161.5849450.662 159.7169460.866 160.116 9498.28158.6869
9539.096160.08339607.123160.91049685.193160.20439702.127158.36559766.477154.4765
9803.732151.08579820.588148.6454 9874.48147.93279911.264146.15269964.022 146.645
10006.73145.178210059.28146.336910116.04143.372310149.99144.666910212.98145.5265
10279.66145.062710333.12145.807210369.38 145.126 10394.7147.039410474.84148.3996
10515.03149.919610525.99147.741110529.64147.725710569.83151.677610640.26154.3981
#Mann= 3 , 0 , 0
9359.704   0.078       09359.704   0.078       010640.26   0.078       0
#XS Ineff= 2 , 0
       0                10516.22       0
Bank Sta=9359.704,10640.26
Exp/Cntr=0.3,0.1

Type RM Length L Ch R = 1 ,4251.455,384.936300,384.936300,384.936300
XS GIS Cut Line= 3
 1240000.9777889621690.4722811281239803.06112224621685.263947785
1238735.35278893622133.180614442
#Sta/Elev= 30
9325.178151.58619383.512151.07229426.178147.57839439.306148.4956 9462.28 146.552
9488.535 146.327 9542.55142.3633 9592.36143.19349652.843 139.8389784.483135.2893
9837.851134.88789852.082133.53819880.545133.18619930.354134.91889955.259133.5673
9980.164134.239910005.07133.031610022.86135.764610033.53136.199410094.01134.2076
10158.06136.098510186.52  133.3710243.44132.8496 10382.2134.541310432.01137.6637
10528.07138.830610584.51144.029410609.95148.542410638.36151.730810681.02153.7934
#Mann= 3 , 0 , 0
9325.178  0.0632       09325.178  0.0632       010681.02  0.0632       0
#XS Ineff= 2 , 0
       0                               0
Bank Sta=9325.178,10681.02
Exp/Cntr=0.3,0.1

Type RM Length L Ch R = 1 ,3866.519,341.464700,341.464700,341.464700
XS GIS Cut Line= 2
1239933.26945555  621450.88894781238667.64445555621706.097281128
#Sta/Elev= 30
9147.288131.08349171.173132.77779201.295132.84089221.376 129.3839301.701132.0947
9328.476 129.8889385.373128.9864 9442.27133.83649462.351133.30879472.392131.7332
9519.248131.60949562.757128.76029609.613130.11699673.204129.72499686.591 128.552
9726.754129.45049756.876 127.742 9773.61128.70239817.119126.85679870.669128.4652
9930.913127.49099947.647128.410410038.01126.582110161.85126.966310235.48129.5193
10305.76134.345610342.58135.145410396.13   140.310418.39138.845910438.39140.0891
#Mann= 3 , 0 , 0
9147.288  0.0943       09147.288  0.0943       010438.39  0.0943       0
#XS Ineff= 2 , 0
       0                               0
Bank Sta=9147.288,10438.39
Exp/Cntr=0.3,0.1

Type RM Length L Ch R = 1 ,3525.054,0.000000,0.000000,0.000000
XS GIS Cut Line= 4
 1239954.1027889621393.5972811281239480.14445558621237.347281128
1238547.85278893621424.8472811281238073.89445555621716.513947785
#Sta/Elev= 30
8933.645130.70298997.507126.5926 9121.87125.95099180.597123.75269232.415125.0856
9301.505123.21679443.855124.24589546.556122.00059580.021123.46639793.288120.4363
9854.437121.52879871.169120.29779884.555122.04279911.328122.208110008.38119.9822
10071.96122.4503 10175.7120.764510235.94124.142210266.06 123.77210359.76127.1051
10393.17126.298510456.31128.045310474.55125.951310525.65128.3981 10691.3128.7958
10803.02134.316610829.98133.213610856.95136.302310883.92133.746210940.17133.7695
#Mann= 3 , 0 , 0
8933.645  0.0933       08933.645  0.0933       010940.17  0.0933       0
#XS Ineff= 2 , 0
       0                               0
Bank Sta=8933.645,10940.17
Exp/Cntr=0.3,0.1